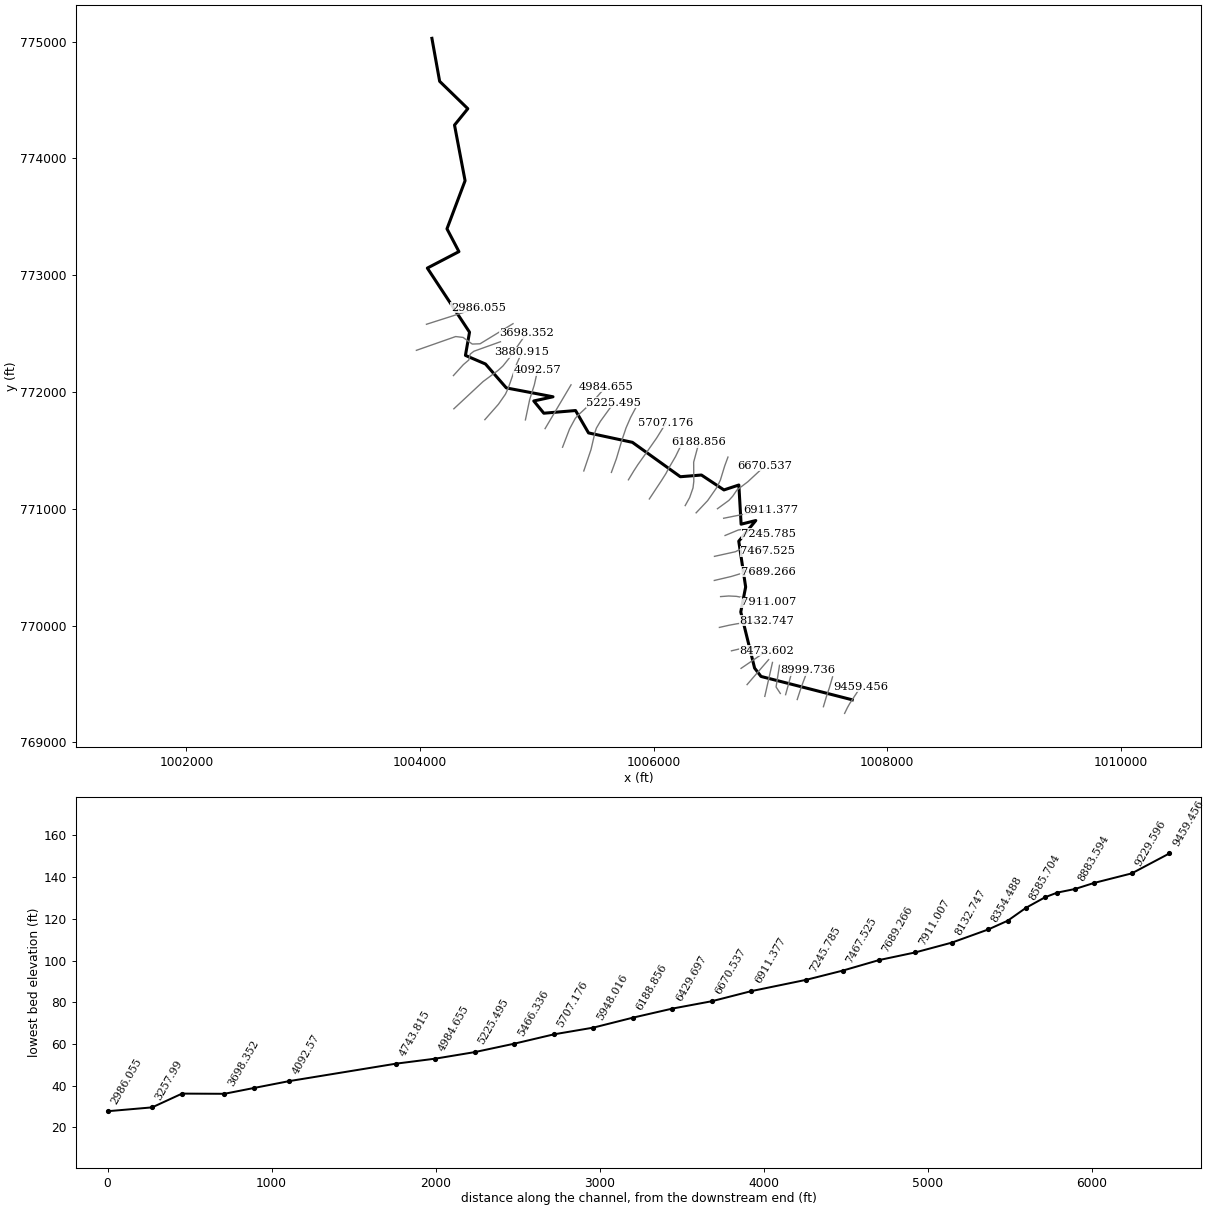
--- 195_ras.prj (project) ---

Proj Title=195
Current Plan=p01
Default Exp/Contr=0.3,0.1
English Units
Geom File=g01
Flow File=f01
Plan File=p01
Y Axis Title=Elevation
X Axis Title(PF)=Main Channel Distance
X Axis Title(XS)=Station
BEGIN DESCRIPTION:
RFD model 195 exported to HEC-RAS
END DESCRIPTION:

--- 195_ras.p01 (plan) ---

Plan Title=Plan 01
Program Version=4.10
Short Identifier=Plan 01
Geom File=g01
Flow File=f01
Subcritical Flow
Calc Critical at every XS
Secant Critical Depth

--- 195_ras.f01 (steady flow) ---

Flow Title=Flow 01
Program Version=5.01
Number of Profiles= 6
Profile Names=10yr,25yr,50yr,100yr,100plus,500yr
River Rch & RM=195,43,9459.456
   84.89  161.81  244.75  336.38  491.11 1127.94
River Rch & RM=195,43,8585.704
   86.54  164.97  249.56  343.01   500.8 1147.15
River Rch & RM=195,43,8354.488
   88.55  168.86  255.49  351.21  512.77    1171
River Rch & RM=195,43,8132.747
  141.78  271.17  411.26  566.17   826.6 1769.31
River Rch & RM=195,43,7911.007
  143.41  274.33  416.08  572.84  836.35 1787.45
River Rch & RM=195,43,7689.266
  165.71  317.45  482.01   664.1  969.59 2032.47
River Rch & RM=195,43,7467.525
  167.99  321.85  488.74  673.43  983.21 2057.28
River Rch & RM=195,43,7245.785
  173.03  331.62  503.69  694.14 1013.44 2112.19
River Rch & RM=195,43,6911.377
  173.73  332.96  505.75  696.99  1017.6 2119.72
River Rch & RM=195,43,6670.537
  198.73  381.53  580.22  800.36 1168.52 2391.48
River Rch & RM=195,43,6429.697
  201.85  387.61  589.58  813.36 1187.51 2425.48
River Rch & RM=195,43,6188.856
  204.64  393.05  597.93  824.97 1204.46 2455.74
River Rch & RM=195,43,5948.016
  207.59  398.79  606.75  837.24 1222.36 2487.62
River Rch & RM=195,43,5707.176
  212.82  408.97  622.39  858.97  1254.1  2543.9
River Rch & RM=195,43,5466.336
  215.41  414.02  630.15  869.76 1269.85 2571.86
River Rch & RM=195,43,5225.495
   238.5   459.1  699.52  966.31 1410.81 2820.09
River Rch & RM=195,43,4984.655
  240.38  462.78  705.18   974.2 1422.33 2840.24
River Rch & RM=195,43,4743.815
  243.66  469.19  715.06  987.96 1442.42 2875.37
River Rch & RM=195,43, 4092.57
   246.3  474.34  723.01  999.05 1458.61 2903.69
River Rch & RM=195,43,3880.915
  247.53  476.77  726.75 1004.26 1466.22 2916.98
River Rch & RM=195,43,3698.352
  354.14  683.64 1043.94 1444.11  2108.4  3992.6
River Rch & RM=195,43, 3440.22
     359  693.16 1058.66 1464.64 2138.38 4042.36
River Rch & RM=195,43, 3257.99
  361.85  698.76 1067.29  1476.7 2155.98 4071.52
River Rch & RM=195,43,2986.055
  364.94  704.84 1076.71 1489.86  2175.2  4103.5
River Rch & RM=195,43,2674.629
  369.39  713.62 1090.32 1508.92 2203.02 4149.84
River Rch & RM=195,43,2447.321
  370.62  716.07 1094.12 1514.25 2210.81 4162.84
River Rch & RM=195,43,2220.014
  371.04  716.88 1095.39 1516.03  2213.4 4167.17
River Rch & RM=195,43,1992.706
  374.47  723.68 1105.94 1530.82    2235 4203.17
River Rch & RM=195,43,1765.399
  403.97  781.82 1196.03 1656.88 2419.04 4506.62
River Rch & RM=195,43,1538.091
  406.13   786.1 1202.66 1666.18 2432.62 4528.98
River Rch & RM=195,43,1310.784
  415.53  804.71 1231.57 1706.72 2491.81  4626.3
River Rch & RM=195,43,1101.134
  416.86  807.35 1235.67 1712.48 2500.22 4640.14
River Rch & RM=195,43,1036.591
  418.81  811.24 1241.76 1721.05 2512.73 4660.87
River Rch & RM=195,43,605.7769
  421.55   816.7 1250.26 1733.03 2530.22 4689.83
River Rch & RM=195,43,403.8513
  422.72  819.03 1253.91 1738.16 2537.71 4702.21
River Rch & RM=195,43,201.9256
  423.37  820.33 1255.93    1741 2541.87 4709.09
River Rch & RM=195,43,       0
  431.99  837.48 1282.66 1778.61 2596.77  4799.5
Boundary for River Rch & Prof#=195,43,1
Up Type= 0
Dn Type= 2
Boundary for River Rch & Prof#=195,43,2
Up Type= 0
Dn Type= 2
Boundary for River Rch & Prof#=195,43,2
Up Type= 0
Dn Type= 2
Boundary for River Rch & Prof#=195,43,2
Up Type= 0
Dn Type= 2
Boundary for River Rch & Prof#=195,43,2
Up Type= 0
Dn Type= 2
Boundary for River Rch & Prof#=195,43,2
Up Type= 0
Dn Type= 2

--- 195_ras.g01 (geometry) ---

Geom Title=195
Program Version=4.10

River Reach=195,43
Reach XY= 30
1007699.93479927 769364.862212731006918.69999968769564.929381217
1006863.71325146769636.4121539041006745.33442059770116.886827479
1006787.14751791770330.9025129981006728.11974013770722.569179677
 1006873.9530735770899.6525130021006748.25862903770868.402513002
1006728.81418461771203.8191796641006601.13442351771161.606759127
 1006408.6752957771289.2358463351006228.11974014771274.652513003
1005817.70307347771569.0969574541005442.11801805771649.667989506
1005330.89751794771841.3191796611005059.36974015771818.402513009
1004973.25862904771923.2636241131005137.98829508771959.080677496
1004738.25632647772035.0313247611004559.93010189772239.660536455
1004388.25260332772313.3140131661004423.25862903772512.152513004
1004062.14751791773060.7636240931004332.54456288773201.872062803
1004230.20307349773396.8747352291004385.17888439773808.777040547
1004294.78640682774285.0691796441004408.67529573774425.346957441
1004167.44265685774659.8521658041004101.25342071775027.690707451

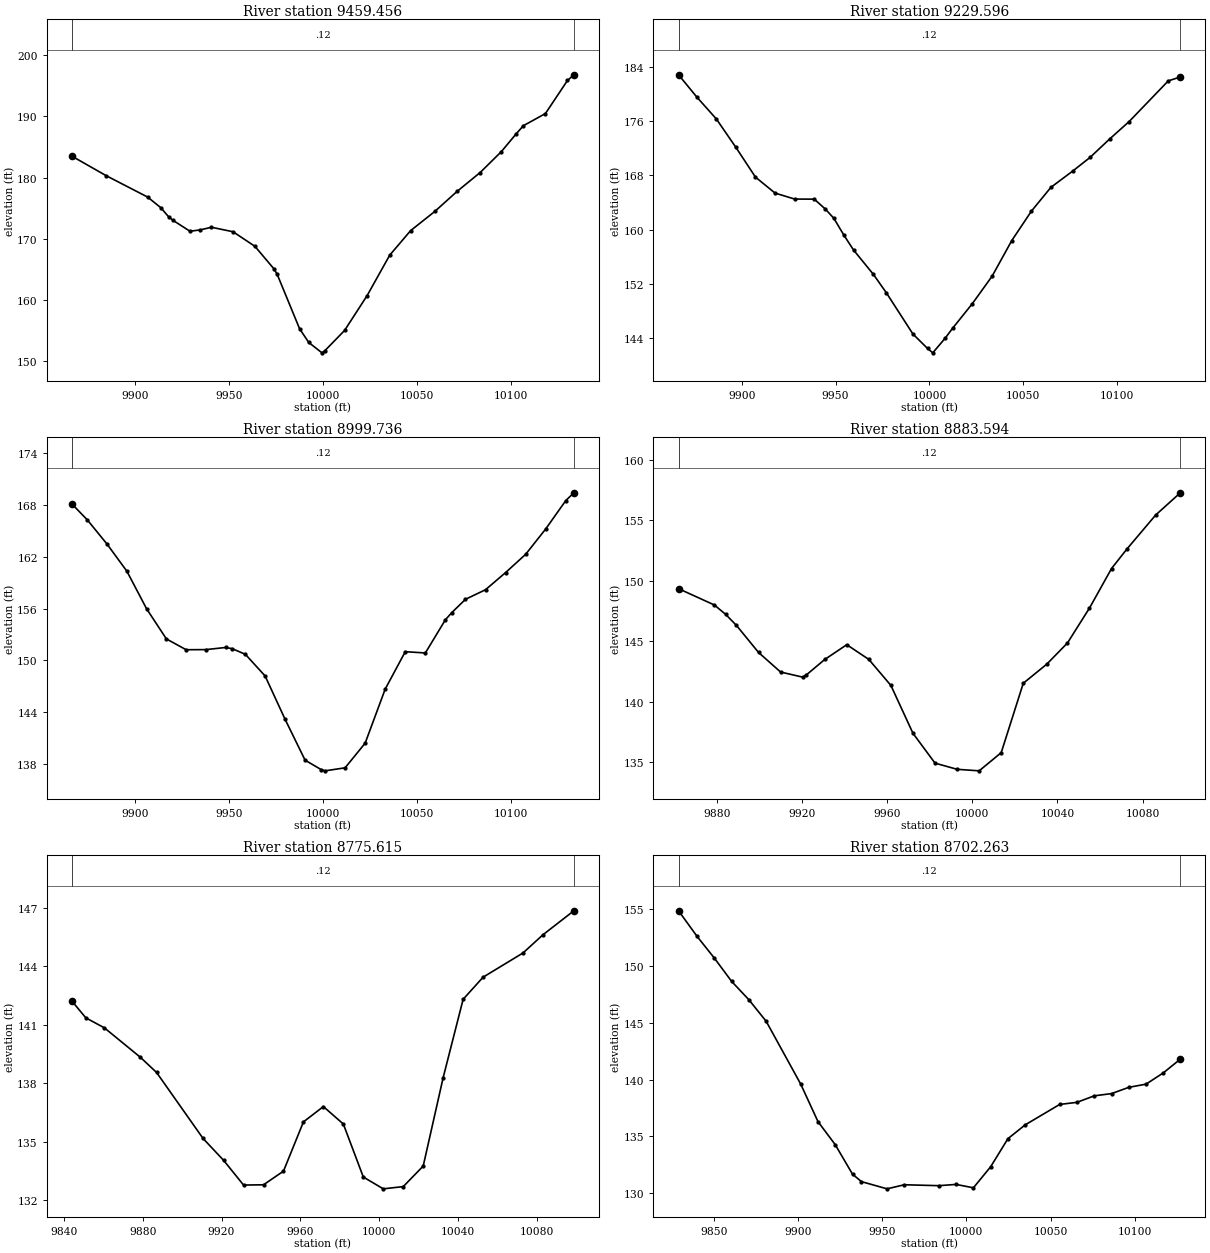
Type RM Length L Ch R = 1 ,9459.456,229.859900,229.859900,229.859900
XS GIS Cut Line= 6
 1007634.4211511769248.7599808711007657.81105035769297.005585872
1007676.58161949769330.5538294131007698.54400614769364.605903422
1007735.79883516769420.4968918341007771.16627604769477.897744005
#Sta/Elev= 30
9866.421183.47119884.469180.31899906.695176.79999913.594175.08979917.808173.5943
9920.037173.03419929.198171.2238 9934.76171.45319940.657171.87829952.116171.1441
 9963.77168.76739974.012165.0448 9975.67164.16569987.569 155.2979992.461153.0614
9999.479151.3732   10001151.716210011.51155.026210023.52 160.71810035.54167.3169
10046.69171.332210059.57174.463310071.46177.746910083.71180.815910094.95184.2143
10102.77187.0897 10106.7188.457510118.44190.439710130.19195.844210133.59196.7741
#Mann= 3 , 0 , 0
9866.421    0.12       09866.421    0.12       010133.59    0.12       0
#XS Ineff= 2 , 0
       0                               0
Bank Sta=9866.421,10133.59
Exp/Cntr=0.3,0.1

Type RM Length L Ch R = 1 ,9229.596,229.859900,229.859900,229.859900
XS GIS Cut Line= 6
1007452.81731646769305.7178785141007477.81400495769390.110796586
1007491.97284304   769432.3783191007492.64237314769434.262922258
1007504.21047038769469.2386377131007531.03158243769561.157240114
#Sta/Elev= 30
9866.407182.85989876.088179.58769886.517 176.3439896.947172.14069907.376167.7427
9917.805165.38679928.235 164.5069938.664164.49159944.516163.04619949.094161.6662
9954.424159.1893 9959.58156.98429970.126153.39529977.048150.66989991.219144.5715
    9999142.442410001.78141.794710008.51144.002810012.31145.416510022.84149.0561
10033.37153.115810043.84158.372110054.26162.705110064.67166.232610076.36168.6539
10085.51170.651610095.93173.369810106.34175.953810127.18181.960210133.59182.5353
#Mann= 3 , 0 , 0
9866.407    0.12       09866.407    0.12       010133.59    0.12       0
#XS Ineff= 2 , 0
       0                               0
Bank Sta=9866.407,10133.59
Exp/Cntr=0.3,0.1

Type RM Length L Ch R = 1 ,8999.736,116.141600,116.141600,116.141600
XS GIS Cut Line= 5
1007228.59929519769367.2602617161007260.22387343769464.383030394
1007270.57719544769493.0167419631007271.26683036769494.894081482
1007317.83697615769619.043565507
#Sta/Elev= 30
 9866.41168.0993 9874.55166.26639885.067163.45679895.583160.3294  9906.1155.9721
9916.617152.48769927.134151.23239937.651151.24459948.167151.4925 9951.68151.3535
9958.684150.70149969.208 148.1899979.842143.17249990.475138.4425    9999137.3527
10001.11137.204310011.79 137.55410022.47140.410310033.15146.676710043.83151.0045
10054.52150.8575 10065.2154.702110068.57155.524310075.88157.072110086.56158.1817
10097.24160.166410107.92162.2811 10118.6165.216810129.28168.5043 10133.6169.4105
#Mann= 3 , 0 , 0
 9866.41    0.12       0 9866.41    0.12       0 10133.6    0.12       0
#XS Ineff= 2 , 0
       0                               0
Bank Sta=9866.41,10133.6
Exp/Cntr=0.3,0.1

Type RM Length L Ch R = 1 ,8883.594,107.978700,107.978700,107.978700
XS GIS Cut Line= 2
1007129.13732308769408.7417970451007191.63732308769636.172352612
#Sta/Elev= 25
9861.904149.35519878.765148.00489884.028 147.2359889.135146.31869899.506144.0861
9909.877142.46729920.247142.04659921.766142.19799930.618143.50339940.989144.7267
 9951.36143.5082 9961.73141.35889972.101 137.4059982.472134.93939992.843134.4312
10003.21 134.30410013.58135.806510023.95141.540210034.98143.1166 10044.7144.8634
10055.07147.753410065.44151.020810072.72152.643310086.18155.439410097.77157.2782
#Mann= 3 , 0 , 0
9861.904    0.12       09861.904    0.12       010097.77    0.12       0
#XS Ineff= 2 , 0
       0                               0
Bank Sta=9861.904,10097.77
Exp/Cntr=0.3,0.1

Type RM Length L Ch R = 1 ,8775.615,73.352500,73.352500,73.352500
XS GIS Cut Line= 3
1007083.99843419769419.158463731 1007047.5401009769474.714019284
1007077.05398977769660.477908179
#Sta/Elev= 23
9844.188142.21219851.175141.36049860.588 140.8479878.815139.33569887.058138.5537
9910.638135.16189921.053134.03879931.178132.76849941.304132.78119951.429133.4824
9961.554136.0141 9971.68136.80119981.805135.90279991.931133.179810002.06132.5735
10012.18132.688210022.31133.744610032.43138.287510042.56142.313910052.68143.4502
10072.93144.694310083.06145.630410098.73146.8629
#Mann= 3 , 0 , 0
9844.188    0.12       09844.188    0.12       010098.73    0.12       0
#XS Ineff= 2 , 0
       09966.282                       0
Bank Sta=9844.188,10098.73
Exp/Cntr=0.3,0.1

Type RM Length L Ch R = 1 ,8702.263,116.559200,116.559200,116.559200
XS GIS Cut Line= 2
1006951.03569385769394.2477732751007016.77420884769684.841890544
#Sta/Elev= 27
 9829.14154.86869840.164152.61079850.416150.69959860.669148.65139870.922147.0333
9881.174145.1389 9901.68139.61089911.932136.30789922.185134.27379932.438 131.679
 9937.75 131.0229952.943130.38729963.196130.74629983.701130.66579993.954130.7766
10004.21130.478210014.46132.329910024.71134.803310034.96136.018910055.47137.8195
10065.72138.003410075.98138.576110086.23138.771710096.48139.323910106.73139.6042
10116.99140.598710127.08 141.804
#Mann= 3 , 0 , 0
 9829.14    0.12       0 9829.14    0.12       010127.08    0.12       0
#XS Ineff= 2 , 0
       09955.013                       0
Bank Sta=9829.14,10127.08
Exp/Cntr=0.3,0.1

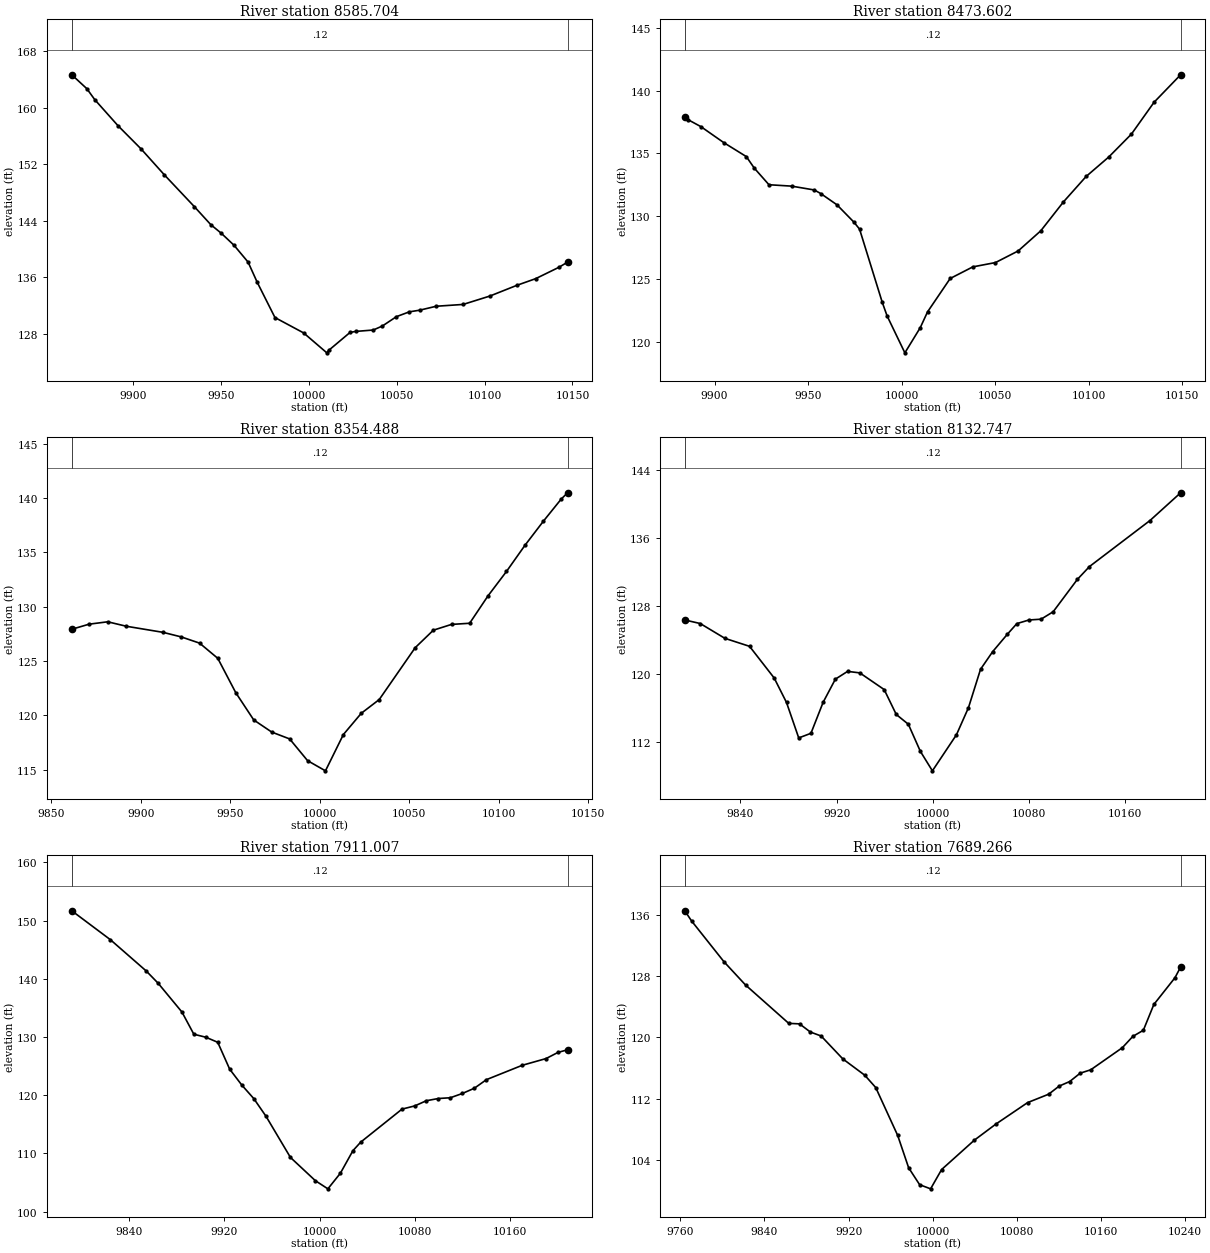
Type RM Length L Ch R = 1 ,8585.704,112.101400,112.101400,112.101400
XS GIS Cut Line= 2
1006799.38889229769495.096631467 1006983.9049513769708.746805057
#Sta/Elev= 30
9864.969164.65679873.554162.68889878.054161.14169891.268157.45889904.481154.1561
9917.694150.49949934.751146.0073 9944.12143.45749950.051142.24999957.333140.5466
 9965.35138.16219970.546135.3099 9980.65130.31879996.973128.144810010.19125.3277
10011.25125.6787 10023.4128.213310026.55128.356410036.61128.554510041.85129.1298
10049.83130.448610057.15131.126310063.04131.360410072.45131.917410087.75132.1731
10103.04133.362610118.34134.8737 10129.1135.821510142.32137.427210147.27138.1588
#Mann= 3 , 0 , 0
9864.969    0.12       09864.969    0.12       010147.27    0.12       0
#XS Ineff= 2 , 0
       0                               0
Bank Sta=9864.969,10147.27
Exp/Cntr=0.3,0.1

Type RM Length L Ch R = 1 ,8473.602,119.114700,119.114700,119.114700
XS GIS Cut Line= 2
1006747.84392029 769634.043947161006966.72329399769783.449662983
#Sta/Elev= 29
9884.091 137.9269885.786137.68239892.755137.11989904.862135.8573 9916.97134.7379
9921.262133.81369929.078132.49469941.185132.38319953.293132.07739956.737 131.794
  9965.4130.89859974.474129.51599977.508128.95529989.615 123.1339992.212122.0441
10001.72119.099310009.95121.105910013.83 122.36110025.94 125.02410038.05125.9498
10050.15126.292810062.26127.217410074.37128.824810086.48131.127210098.58133.1507
10110.69134.7042 10122.8136.528710134.91139.0679 10149.1141.2562
#Mann= 3 , 0 , 0
9884.091    0.12       09884.091    0.12       0 10149.1    0.12       0
#XS Ineff= 2 , 0
       0                               0
Bank Sta=9884.091,10149.1
Exp/Cntr=0.3,0.1

Type RM Length L Ch R = 1 ,8354.488,221.740500,221.740500,221.740500
XS GIS Cut Line= 6
1006665.64880188769784.2548689461006743.26562768769802.532265187
1006775.64551824769805.6055464961006851.73927564 769807.08475375
1006889.04577371769813.3103073281006938.06629949769825.873998159
#Sta/Elev= 27
9861.548127.91659871.248128.38539881.622128.60389891.995 128.1949912.527127.6325
9922.721127.21079932.915126.64079943.084125.24379953.129122.08029963.174119.5706
9973.219118.45579983.222117.82489993.222115.827310003.22114.888110013.22118.2278
10023.22120.183210033.25121.448410053.33126.220710063.47127.831110073.61128.3629
10083.74128.468310093.99130.988810104.32133.237910114.64135.644710124.96137.8695
10134.93139.908810138.45140.4763
#Mann= 3 , 0 , 0
9861.548    0.12       09861.548    0.12       010138.45    0.12       0
#XS Ineff= 2 , 0
       09905.157                       0
Bank Sta=9861.548,10138.45
Exp/Cntr=0.3,0.1

Type RM Length L Ch R = 1 ,8132.747,221.740500,221.740500,221.740500
XS GIS Cut Line= 6
1006562.43007655769984.5852341631006646.44337631770003.562602888
1006720.12062218770017.0516383021006747.06709645770019.902494865
1006803.02979882770022.0854759231006970.30553575770042.294709346
#Sta/Elev= 30
9793.687126.37459806.573125.95279827.077124.20759847.581123.26639868.085119.5314
9878.337116.64859888.516112.46749898.682113.01339908.848116.67659919.014119.3976
9929.181120.31319939.347120.13499959.625118.16819969.681115.23279979.737114.0783
9989.751110.88139999.755108.587510019.78112.841610029.79116.042810039.81120.5595
10049.88122.633210062.12124.689110070.03125.9443 10080.1126.371710090.17126.4653
10100.25127.339810120.39 131.15710130.46132.670810180.83138.097510206.32 141.368
#Mann= 3 , 0 , 0
9793.687    0.12       09793.687    0.12       010206.32    0.12       0
#XS Ineff= 2 , 0
       09948.127                       0
Bank Sta=9793.687,10206.32
Exp/Cntr=0.3,0.1

Type RM Length L Ch R = 1 ,7911.007,221.740600,221.740600,221.740600
XS GIS Cut Line= 6
 1006572.6253574770248.4879838141006642.46167258770253.729042913
1006707.84401018770250.6307955371006748.43103823770242.881993524
1006855.47417881770212.3261829281006983.05408046770199.018974694
#Sta/Elev= 30
9791.707 151.6999824.173146.72529854.258 141.3549864.279139.2451 9884.28 134.295
 9894.28130.47949904.315129.96769914.351129.09639924.387124.47519934.526121.7555
9944.707 119.4029954.888116.38569975.438109.30749996.376105.310210006.89103.9095
 10017.4 106.59310027.92110.462810034.49 111.93910069.19117.611910079.95118.1657
10089.58119.050210099.68119.433710109.79119.564710119.89120.2998   10130121.2048
 10140.1122.674610170.18125.141510190.22126.300410200.25127.359710208.32127.8107
#Mann= 3 , 0 , 0
9791.707    0.12       09791.707    0.12       010208.32    0.12       0
#XS Ineff= 2 , 0
       0                               0
Bank Sta=9791.707,10208.32
Exp/Cntr=0.3,0.1

Type RM Length L Ch R = 1 ,7689.266,221.740500,221.740500,221.740500
XS GIS Cut Line= 6
 1006518.7626003 770386.602608691006663.13331771770420.502337617
1006767.72827439 770452.085996291006805.31003226770460.518699461
1006882.16562646770465.9617334691006980.42288115770462.654302862
#Sta/Elev= 30
9764.236136.55099770.643135.23149801.459129.89969822.003126.85429863.091 121.843
9873.363121.77649883.635120.71129893.907120.19119914.482117.20339935.358115.0699
9945.796  113.469966.672107.2058 9977.11102.97379987.548100.76619997.986100.2236
10008.47102.7466 10039.5106.572610059.99108.677410090.19111.487810110.24112.5869
10120.24 113.64610130.25114.242910140.25115.335410150.26115.775710180.28 118.659
10190.28120.137710200.29 120.94110210.29124.3151 10230.3127.793510235.73129.1985
#Mann= 3 , 0 , 0
9764.236    0.12       09764.236    0.12       010235.73    0.12       0
#XS Ineff= 2 , 0
       0                               0
Bank Sta=9764.236,10235.73
Exp/Cntr=0.3,0.1

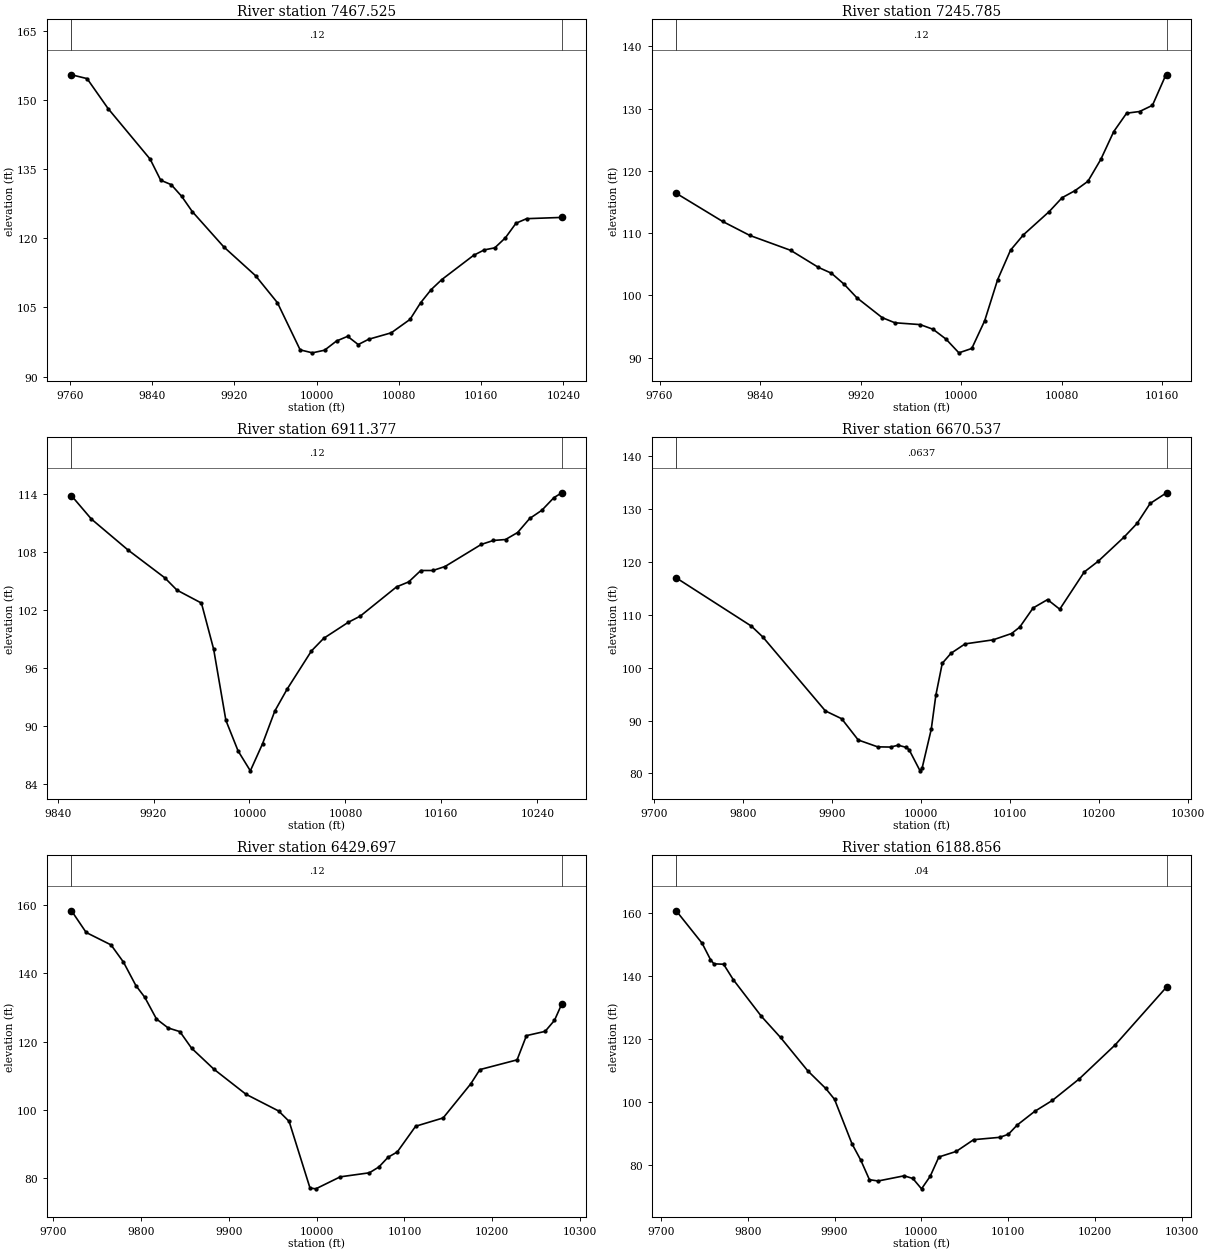
Type RM Length L Ch R = 1 ,7467.525,221.740500,221.740500,221.740500
XS GIS Cut Line= 6
1006520.17747943770592.9747411011006699.68693035770632.616615329
1006767.12361111770667.7123446751006794.42146032770674.454718879
1006838.42538224770670.7991258091006978.20383847770635.410650196
#Sta/Elev= 30
9761.542155.5021  9776.7154.67129797.153148.16539838.059137.18169848.285132.6208
9858.511131.66129868.738129.11289878.964125.82559909.643118.15169940.559111.8976
 9961.86106.02719983.91395.806829995.81695.1605310007.6595.7330610019.28 97.7303
10030.0898.74237 10040.496.9538610050.5398.1060910072.5299.5058110090.76102.4149
   10101106.005510111.32 108.88110121.64111.055510152.58116.3178 10162.9117.4964
10173.21117.947210183.53120.125810193.84123.292110204.16124.275310238.41124.5481
#Mann= 3 , 0 , 0
9761.542    0.12       09761.542    0.12       010238.41    0.12       0
#XS Ineff= 2 , 0
       0                               0
Bank Sta=9761.542,10238.41
Exp/Cntr=0.3,0.1

Type RM Length L Ch R = 1 ,7245.785,334.407800,334.407800,334.407800
XS GIS Cut Line= 4
1006610.90815645770771.5890192841006723.75537863770818.464019269
1006798.40815645 770828.880685941006985.90815645770785.477908179
#Sta/Elev= 30
9773.267116.39849810.183111.8724 9831.84109.62279864.325107.23019886.432104.4881
9896.719103.55849906.816 101.7939916.91399.625319937.10796.421779947.20495.59501
9967.39795.299439977.60594.546789987.86992.974459998.13390.76442 10008.4  91.468
10018.6695.9214810028.93102.505410039.19107.250710049.46109.720110069.98113.4577
10080.25115.685710090.51116.818710100.78118.321410111.04121.845210121.31126.3062
10131.57129.262410141.84129.5274 10152.1130.522810162.36135.2215 10163.3135.4301
#Mann= 3 , 0 , 0
9773.267    0.12       09773.267    0.12       0 10163.3    0.12       0
#XS Ineff= 2 , 0
       0                               0
Bank Sta=9773.267,10163.3
Exp/Cntr=0.3,0.1

Type RM Length L Ch R = 1 ,6911.377,240.840300,240.840300,240.840300
XS GIS Cut Line= 3
1006598.75537866770919.1584637311006824.44982308770964.297352612
1007001.53315645770988.602908179
#Sta/Elev= 30
9851.587 113.8369868.153111.42189898.747108.21339929.341105.3415 9939.54104.0596
9959.936102.72039970.13497.943769980.33290.57693 9990.5387.4031910000.7385.34722
10010.9388.1577110021.1291.5354110031.3293.7911410051.7297.7700510061.9299.07117
10082.31100.7221 10092.4101.369610122.68104.398610132.78104.912810142.87106.0913
10152.96106.093310163.06106.503710193.34108.795210203.43109.203110213.53   109.3
10223.62110.025910233.71111.481410243.81112.3281 10253.9113.639510260.49114.1408
#Mann= 3 , 0 , 0
9851.587    0.12       09851.587    0.12       010260.49    0.12       0
#XS Ineff= 2 , 0
       0                               0
Bank Sta=9851.587,10260.49
Exp/Cntr=0.3,0.1

Type RM Length L Ch R = 1 ,6670.537,240.840200,240.840200,240.840200
XS GIS Cut Line= 6
1006545.79245289771000.7394456941006643.63288495771072.036655754
1006676.14036162771107.6800583161006712.51870828771160.873059267
 1006806.0407804771231.8555248091006952.36265863 771367.63900456
#Sta/Elev= 30
9724.538116.97919809.002107.85679821.823105.8148 9892.2191.824219910.50390.34891
9929.12386.32983 9950.9885.031729965.57784.991479973.93685.341499982.64384.95419
9986.27784.499839998.61780.49716   1000181.0609710011.1888.3371510016.3794.79383
10023.56100.817810033.34102.711910049.23104.4945 10080.7105.258110101.45106.4526
10110.67 107.66710125.65111.278910141.89112.865910155.62111.046710183.09118.0782
10198.84120.117210228.01124.6995 10242.6127.282410257.18131.030810275.62133.0573
#Mann= 3 , 0 , 0
9724.538  0.0637       09724.538  0.0637       010275.62  0.0637       0
#XS Ineff= 2 , 0
       0                               0
Bank Sta=9724.538,10275.62
Exp/Cntr=0.3,0.1

Type RM Length L Ch R = 1 ,6429.697,240.840300,240.840300,240.840300
XS GIS Cut Line= 6
1006363.19854725770965.7437363681006461.55014025771069.901656034
 1006540.9166439771183.7946390431006570.65816897771245.743410858
1006607.54317937771366.4765543821006635.67935733771442.843736602
#Sta/Elev= 30
9720.678158.26149737.395151.91689765.727148.28379779.893143.24839794.059136.3846
9804.169132.96619817.494126.61999830.819124.00099844.143122.93259857.468118.0938
9882.931111.93879919.445104.61779956.70999.718099968.60696.692599992.40177.20546
    999976.96112 10026.9 80.471310060.0481.64995 10070.983.3526310081.3886.20608
10091.8487.7427710112.7595.2608410144.12 97.694610175.49 107.63410185.94111.8234
10228.34114.6725   10239121.756210260.31 123.00410270.97126.233310279.33131.0541
#Mann= 3 , 0 , 0
9720.678    0.12       09720.678    0.12       010279.33    0.12       0
#XS Ineff= 2 , 0
       0                               0
Bank Sta=9720.678,10279.33
Exp/Cntr=0.3,0.1

Type RM Length L Ch R = 1 ,6188.856,240.840200,240.840200,240.840200
XS GIS Cut Line= 6
1006269.63364817771027.5972561481006307.98425978771097.009110094
1006336.49592207771178.7466711661006343.27424524771234.530804729
1006342.08679209771399.3640710631006387.99179654 771570.90043814
#Sta/Elev= 30
9717.373160.68069747.284150.38159756.877145.23659760.815143.87649772.033143.7481
 9783.25 138.8329815.532127.26799837.668120.54979869.125109.96769889.757104.4021
9899.906100.96299920.10486.835479930.12881.71734 9940.15 75.5061 9950.1675.09401
 9980.1976.73518  9990.275.8855910000.21 72.607410010.2176.5881910020.2282.70028
10040.2384.4607210060.2688.1784810090.3188.9218110100.3389.8863510110.4192.79973
10130.6597.1408210151.07100.617410181.84107.390710223.58118.234710282.65136.5182
#Mann= 3 , 0 , 0
9717.373    0.04       09717.373    0.04       010282.65    0.04       0
#XS Ineff= 2 , 0
       0                               0
Bank Sta=9717.373,10282.65
Exp/Cntr=0.3,0.1

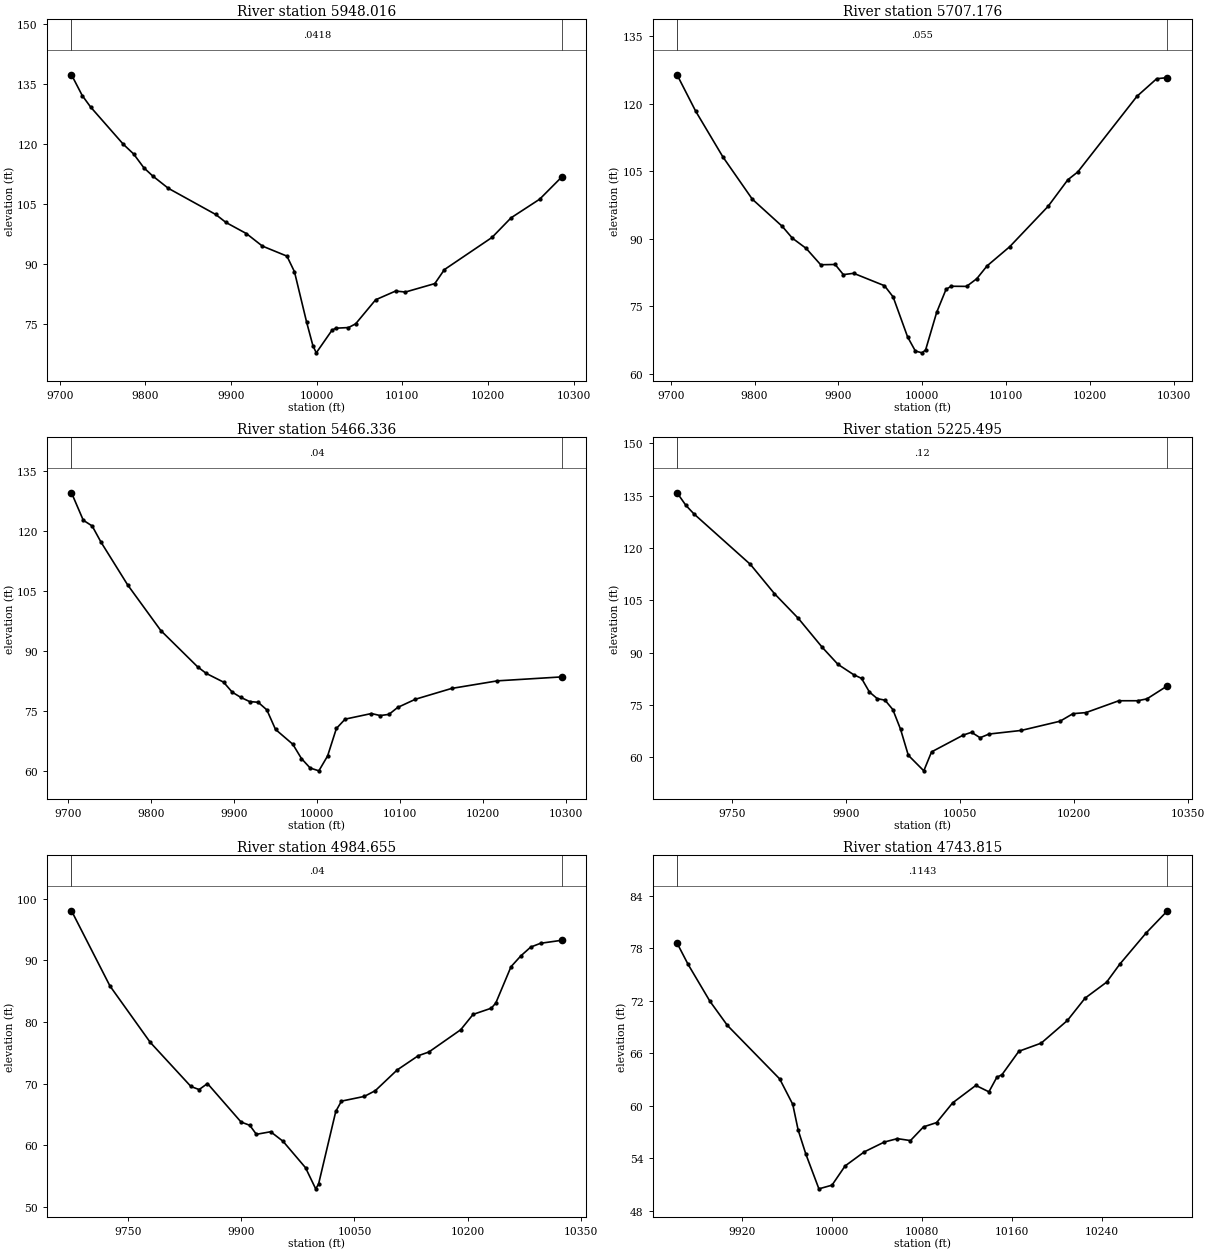
Type RM Length L Ch R = 1 ,5948.016,240.840300,240.840300,240.840300
XS GIS Cut Line= 6
1005962.70921704771084.5414979931006067.71255073771243.382292769
1006104.94526546771302.3242091341006125.22218282771341.664314387
1006186.38435131771446.453087549 1006250.5709984771578.334618345
#Sta/Elev= 30
9713.792137.24389726.329132.0581 9736.08129.20379774.279119.89399786.267117.4875
9798.254114.02949808.615111.97889826.749108.91399882.167102.36789894.154100.3701
9917.94497.604179936.573  94.4849965.256 91.97569974.03788.08199 9988.2375.49215
 9995.5869.615299999.50767.8331810017.69 73.431410022.0873.98198 10037.174.14366
10045.4475.07163 10068.881.0777310092.0783.2562510103.5283.0100310137.8785.12126
10149.0488.6085810204.6496.6427610226.89101.540710260.25106.1877 10286.2 111.766
#Mann= 3 , 0 , 0
9713.792  0.0418       09713.792  0.0418       0 10286.2  0.0418       0
#XS Ineff= 2 , 0
       0                               0
Bank Sta=9713.792,10286.2
Exp/Cntr=0.3,0.1

Type RM Length L Ch R = 1 ,5707.176,240.840200,240.840200,240.840200
XS GIS Cut Line= 6
1005783.48663128771248.2145716121005828.47615078771322.657469487
1005863.55876783771376.8288131211005945.70254746771492.534829908
1006024.77070571771605.4245894141006105.78281316771735.903067626
#Sta/Elev= 30
9707.579126.46359729.839118.35419762.245108.19529797.35298.785159833.09492.73565
9845.00890.13192 9861.59 87.83359878.86684.203119896.14384.261369905.91182.00258
9918.17482.299749954.96379.538489965.24777.053689982.52368.150469991.75365.01544
9999.79464.6054410004.0165.2624510017.2173.6176810028.43 78.758810034.6479.41598
10052.8579.3884510065.0581.0990210077.2683.9401810104.3688.22562 10150.197.20218
10173.64103.111810185.41104.834210256.03121.671510279.57125.583710292.41125.8355
#Mann= 3 , 0 , 0
9707.579   0.055       09707.579   0.055       010292.41   0.055       0
#XS Ineff= 2 , 0
       0                               0
Bank Sta=9707.579,10292.41
Exp/Cntr=0.3,0.1

Type RM Length L Ch R = 1 ,5466.336,240.840300,240.840300,240.840300
XS GIS Cut Line= 6
1005637.82051991771311.7349438081005680.71474378771429.419624021
1005726.38256038771583.1759760571005763.21560381771692.753930099
1005801.96255755771781.8981118451005845.44561548771863.492488914
#Sta/Elev= 30
9704.509129.50479718.706122.65279729.409121.22629740.112117.17589772.221106.5095
9812.15595.13541 9856.4786.092919866.90284.443519887.76582.263969898.19779.76368
9908.62978.452639919.06177.429969929.492 77.23499939.92475.340919950.35670.47213
 9971.2266.769529981.65163.194069992.09460.8462310002.5960.1394810013.1563.86442
10023.7170.7108810034.2673.0382410065.9374.4315410076.4973.9327810087.0474.22257
 10097.675.95688   1011978.00483 10162.6 80.696810217.8682.5915310295.4783.57663
#Mann= 3 , 0 , 0
9704.509    0.04       09704.509    0.04       010295.47    0.04       0
#XS Ineff= 2 , 0
       0                               0
Bank Sta=9704.509,10295.47
Exp/Cntr=0.3,0.1

Type RM Length L Ch R = 1 ,5225.495,240.840200,240.840200,240.840200
XS GIS Cut Line= 6
1005401.45705011771324.0376526591005463.42308554771507.643476721
1005498.38195474771658.6298523681005509.41511722771690.924988857
1005543.57843387771749.041599493 1005657.9714992771906.821982123
#Sta/Elev= 30
9677.295135.8483 9688.94132.23639699.563129.78729773.925115.27939805.442106.9245
9836.89299.827069868.34291.530669889.06986.633899909.76183.670379920.10682.61496
9930.45278.706089940.79876.807479951.01776.356949961.21573.688979971.41468.03882
9981.61360.5703410002.02 56.096210012.2461.5337510054.0366.3619310064.8767.14744
10076.1165.5908610087.8166.64756 10130.267.6836910181.3170.3282710198.3472.49645
10215.3872.7990410258.6576.1957510283.36 76.200410295.7176.7421610322.6680.48694
#Mann= 3 , 0 , 0
9677.295    0.12       09677.295    0.12       010322.66    0.12       0
#XS Ineff= 2 , 0
       0                               0
Bank Sta=9677.295,10322.66
Exp/Cntr=0.3,0.1

Type RM Length L Ch R = 1 ,4984.655,240.840300,240.840300,240.840300
XS GIS Cut Line= 6
1005219.59776202 771527.23886881 1005279.6946298771683.702696952
  1005328.215645771773.6324584041005351.19831402771800.010650227
1005482.33625165771921.4637232431005591.36636734772046.602950907
#Sta/Elev= 30
9675.163 98.06519726.10585.866869779.43576.729689833.39469.559889844.23369.06078
9855.35170.036449899.82263.795369911.38163.261149920.10661.799479939.02662.21816
9955.438 60.67039985.22256.382439998.70652.9549810002.5153.7264910025.3165.51502
10032.8367.1839510063.1467.95098 10077.768.88223 10106.6 72.237410134.6174.55225
10148.6275.1506110190.8378.7636810207.2481.2534110231.3682.2608810237.3283.09781
10257.4988.9923110270.5690.7558910283.6292.1770210296.6992.7933510324.9193.28192
#Mann= 3 , 0 , 0
9675.163    0.04       09675.163    0.04       010324.91    0.04       0
#XS Ineff= 2 , 0
       0                               0
Bank Sta=9675.163,10324.91
Exp/Cntr=0.3,0.1

Type RM Length L Ch R = 1 ,4743.815,651.244600,651.244600,651.244600
XS GIS Cut Line= 2
1005070.10954532771686.5195748361005292.33176756772061.519574821
#Sta/Elev= 30
9862.16478.594789872.02176.153899891.37271.954489906.89369.196579953.38963.08447
9965.01360.181639969.83457.232469976.63754.503199988.26150.532219999.88550.95155
10011.51 53.143110028.6854.7602210046.3855.87588   1005856.2648710069.63 56.0423
10081.2557.6099910092.8858.0965810107.1460.3513610127.7562.3407510139.37 61.6099
10146.3763.26462   1015163.5714910165.99 66.241210185.8767.1724310209.1269.75549
10224.8372.3060810243.9974.1317510255.6176.1722310278.8679.7149510298.0682.28296
#Mann= 3 , 0 , 0
9862.164  0.1143       09862.164  0.1143       010298.06  0.1143       0
#XS Ineff= 2 , 0
       0                               0
Bank Sta=9862.164,10298.06
Exp/Cntr=0.3,0.1

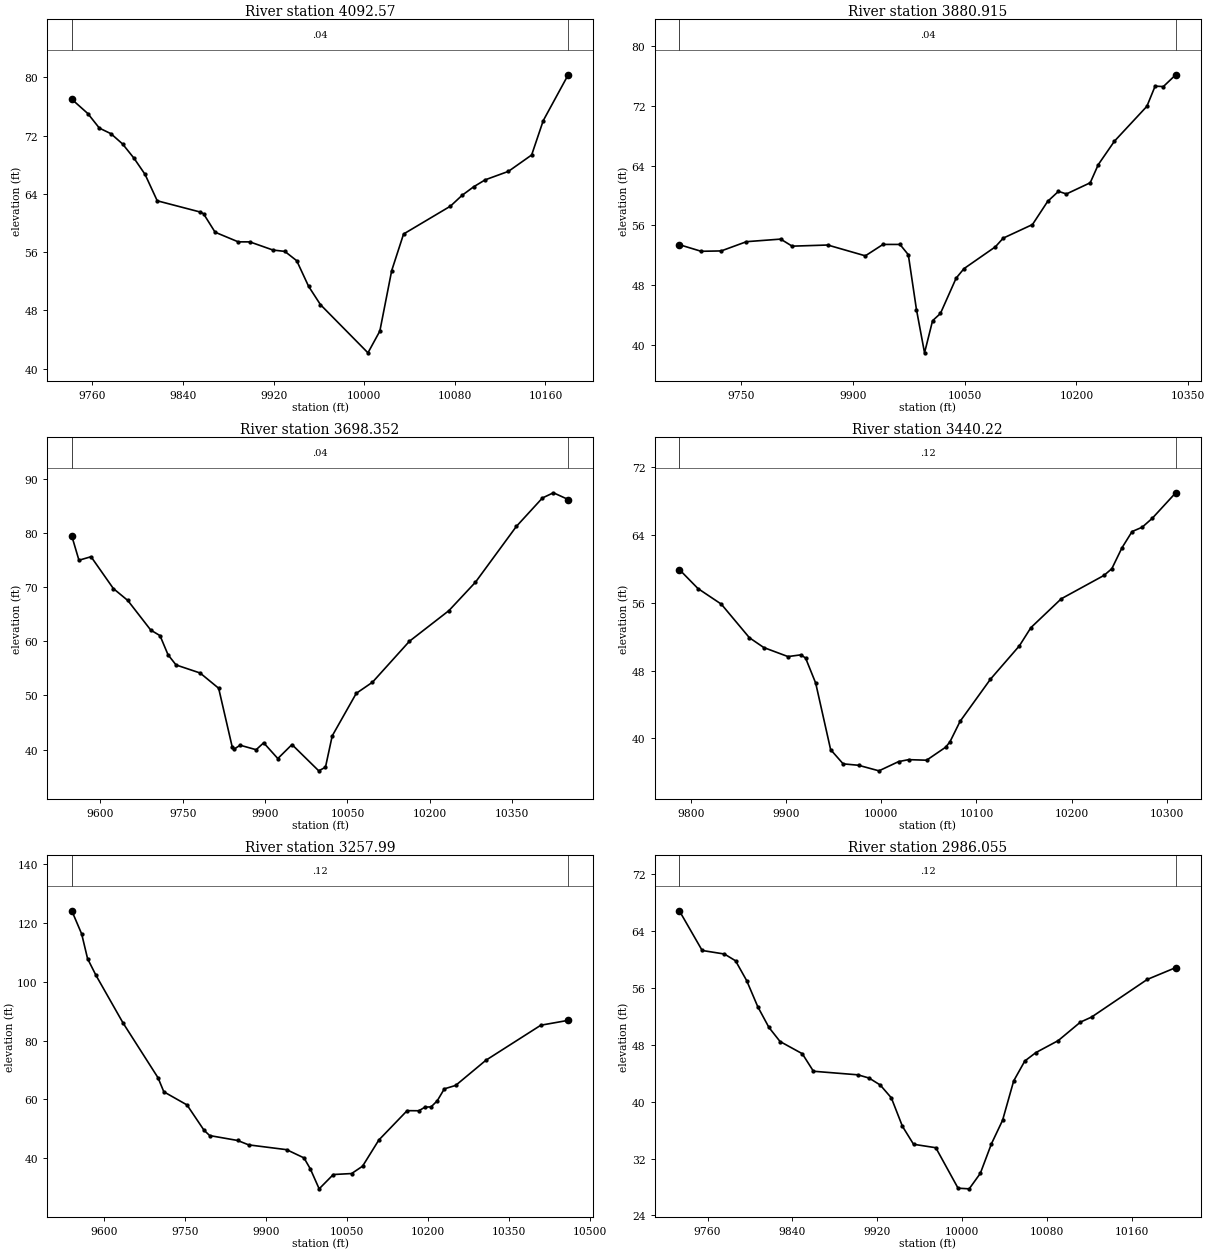
Type RM Length L Ch R = 1 , 4092.57,211.655400,211.655400,211.655400
XS GIS Cut Line= 4
1004901.70676756771761.172352612 1004938.1651009771934.783463731
1004978.09565642772061.5195748211005005.87343419772186.519574821
#Sta/Elev= 30
9741.74376.990389755.872 75.0321 9766.0973.029489776.308  72.2629786.52670.86074
9796.74568.879459806.42566.673729817.18163.046299855.082 61.50579858.05361.26899
9868.27158.731729888.70857.406329898.92657.403789919.36856.282659929.85256.09587
9940.33754.817399950.82251.301819961.30648.7786910003.2442.1625510013.7345.14739
10024.21 53.4603 10034.758.4848110076.0762.3098410086.3263.7930210096.5664.96768
 10106.865.9286310127.2967.0897610147.7869.3387110158.0274.0573210180.07 80.3553
#Mann= 3 , 0 , 0
9741.743    0.04       09741.743    0.04       010180.07    0.04       0
#XS Ineff= 2 , 0
       0                               0
Bank Sta=9741.743,10180.07
Exp/Cntr=0.3,0.1

Type RM Length L Ch R = 1 ,3880.915,182.563200,182.563200,182.563200
XS GIS Cut Line= 6
 1004554.5445049771763.2985548691004670.50764772 771894.81524478
1004730.74206569771981.1525051611004755.57450803772035.238489785
1004825.71929572772237.5177603141004871.07870805 772340.05967048
#Sta/Elev= 30
9666.73553.405839695.99252.519479722.95552.567939756.87853.806899802.78954.15229
9818.19853.206259865.96653.359229916.503 51.91059940.18253.438479962.98553.43762
9974.19152.05955 9985.1244.717369995.98338.9164910006.7743.2200810017.3144.18792
 10038.448.9214710048.9450.19442 10091.153.1193610101.6454.28322 10140.956.10098
10161.3259.2066410175.82 60.549310186.48 60.199210218.4661.6972810229.26 64.1285
10250.96 67.267610294.5471.9392810305.5974.6405310316.6574.58429 10333.376.16393
#Mann= 3 , 0 , 0
9666.735    0.04       09666.735    0.04       0 10333.3    0.04       0
#XS Ineff= 2 , 0
       0 9950.35                       0
Bank Sta=9666.735,10333.3
Exp/Cntr=0.3,0.1

Type RM Length L Ch R = 1 ,3698.352,258.131900,258.131900,258.131900
XS GIS Cut Line= 6
1004289.15936074771856.2216358141004539.25205826772089.297806905
1004667.63408501772184.6234767671004708.96753359772222.447427574
1004759.65270969772285.6767165281004911.05026153772502.672977105
#Sta/Elev= 30
9548.15579.445129561.16174.971299583.17575.620049623.83269.738169650.05967.54409
9691.836 62.07999708.76861.04617 9723.3557.517389737.93355.638169781.68154.15294
9815.48951.337569840.01240.570239842.96840.055589854.59540.82011 9883.7639.98769
9897.43241.265579923.19738.356629948.96140.939459997.70936.0885110009.9436.76224
10022.22  42.54310066.0150.3987310095.5152.44937 10162.860.0142310234.6565.66826
10282.93 70.9078 10357.481.2093410404.9286.4691610424.8987.4243710451.8386.18262
#Mann= 3 , 0 , 0
9548.155    0.04       09548.155    0.04       010451.83    0.04       0
#XS Ineff= 2 , 0
       09942.764                       0
Bank Sta=9548.155,10451.83
Exp/Cntr=0.3,0.1

Type RM Length L Ch R = 1 , 3440.22,182.229600,182.229600,182.229600
XS GIS Cut Line= 6
1004285.38732311772140.5126303881004370.45676753772234.262630388
1004417.33176753 772274.193185941004429.48454535772324.540408179
1004460.73454535772348.845963717 1004688.1651009772430.443185955
#Sta/Elev= 30
9788.03859.918189807.601 57.67599832.10555.836229861.61451.874139876.74950.71646
9902.12449.653819915.76949.85992  9920.649.47493 9931.19 46.52829946.87338.68149
9960.009 37.00519976.20936.835829997.61336.1807710018.1937.2680910028.7537.50039
10047.6637.4348410067.5938.9634410072.1239.5913110082.7542.0084510114.6246.97931
10145.0450.9205810157.1253.0641210188.99 56.467110233.8759.2236810242.1160.01738
10252.73 62.476410263.3664.3959410273.9864.9074510284.61 65.964710309.2268.96817
#Mann= 3 , 0 , 0
9788.038    0.12       09788.038    0.12       010309.22    0.12       0
#XS Ineff= 2 , 0
       09944.791                       0
Bank Sta=9788.038,10309.22
Exp/Cntr=0.3,0.1

Type RM Length L Ch R = 1 , 3257.99,271.934700,271.934700,271.934700
XS GIS Cut Line= 6
1003968.32185277 772356.671065611004304.69646396772474.734304862
1004368.17882581 772467.119769381004446.55223411 772410.40699067
1004513.46689116772412.793043473 1004795.6567383772584.846022694
#Sta/Elev= 30
9539.812 124.1859558.088116.31749569.046 107.9029584.633102.22459634.79586.02005
9699.69667.368149710.43262.596069753.377 58.13099784.97949.510239795.49847.70089
9847.27846.035469867.71844.539659938.10642.907129970.31540.104789982.13136.33052
9998.43129.5812710024.6734.45243 10058.634.78371 10078.937.2878110109.1146.20157
 10161.556.1809610183.28 56.145910194.5757.3764310205.9557.4694610217.3359.52846
10230.4963.5969110251.4764.7665310307.6373.3384310409.3685.2466110460.1786.91039
#Mann= 3 , 0 , 0
9539.812    0.12       09539.812    0.12       010460.17    0.12       0
#XS Ineff= 2 , 0
       0                               0
Bank Sta=9539.812,10460.17
Exp/Cntr=0.3,0.1

Type RM Length L Ch R = 1 ,2986.055,311.426700,311.426700,311.426700
XS GIS Cut Line= 2
1004054.48454535772579.7487415081004500.66510093772722.109852582
#Sta/Elev= 30
9733.35366.878379754.88861.290649775.88160.788299786.37859.838229796.87457.04845
9807.37153.365139817.86850.458359828.36448.473419849.35846.753789859.85444.28468
9901.84143.781519912.33843.328659922.83442.353029933.33140.547659943.82836.53425
9954.32434.003679975.31833.517269996.31127.8198410006.8127.72936 10017.329.90476
 10027.834.07212 10038.337.3774910048.7942.9258210059.29 45.731610069.7946.91795
10090.7848.5978110111.7751.2047610122.2751.9116910174.7557.2078310201.6958.87709
#Mann= 3 , 0 , 0
9733.353    0.12       09733.353    0.12       010201.69    0.12       0
#XS Ineff= 2 , 0
       0                               0
Bank Sta=9733.353,10201.69
Exp/Cntr=0.3,0.1