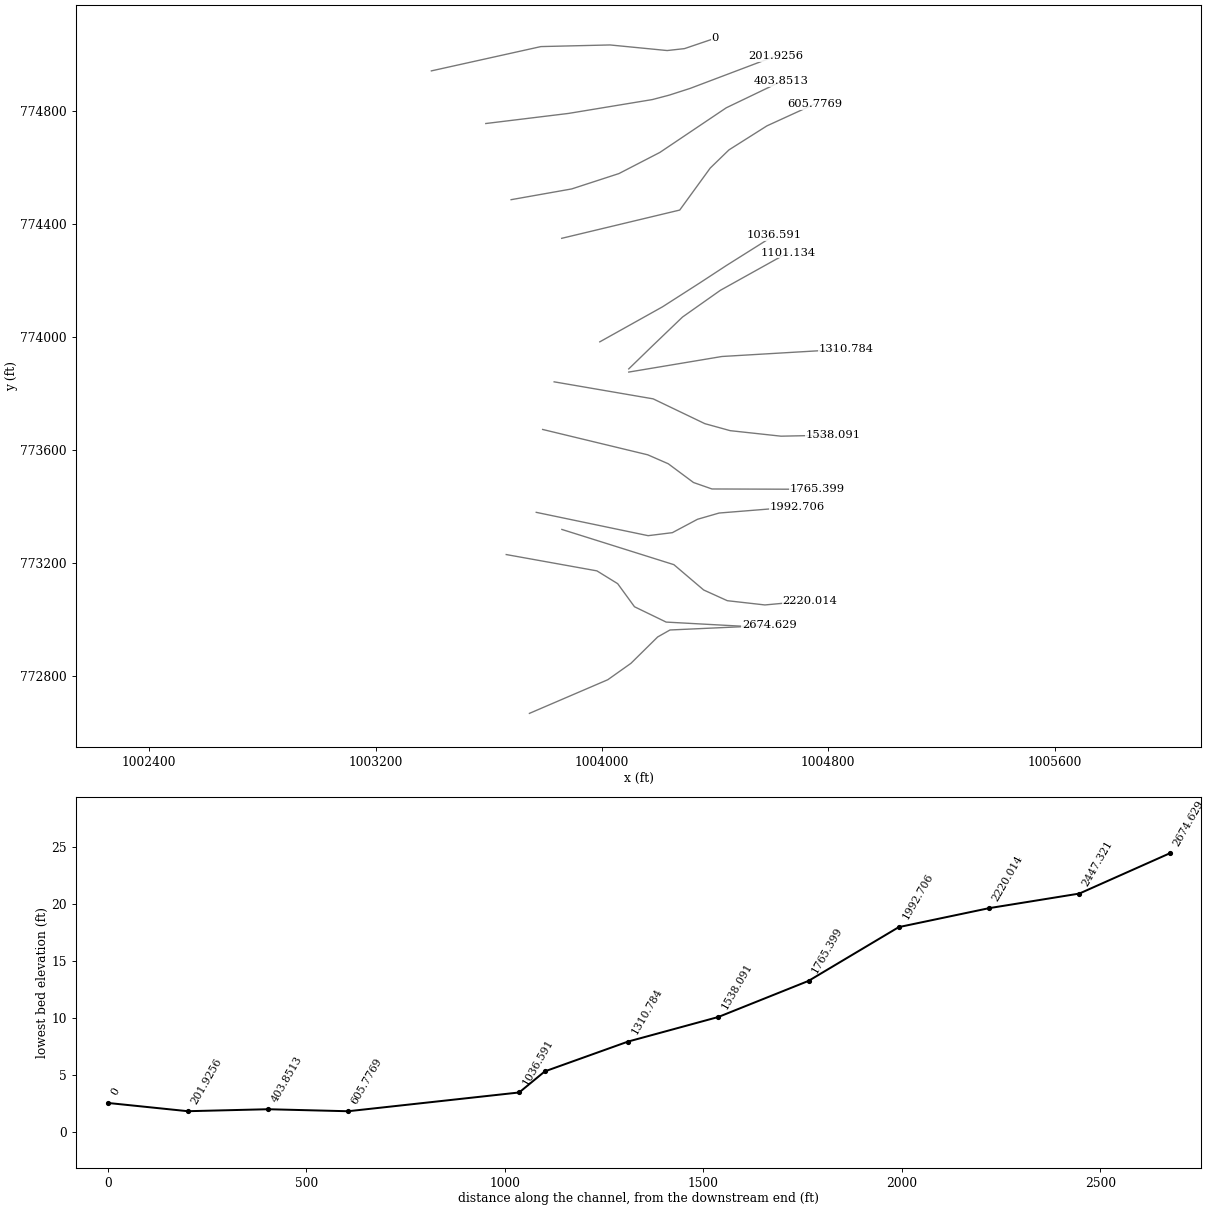
HEC-RAS study 195_ras.prj: 195

--- 195_ras.g01 (geometry) --- (continued)

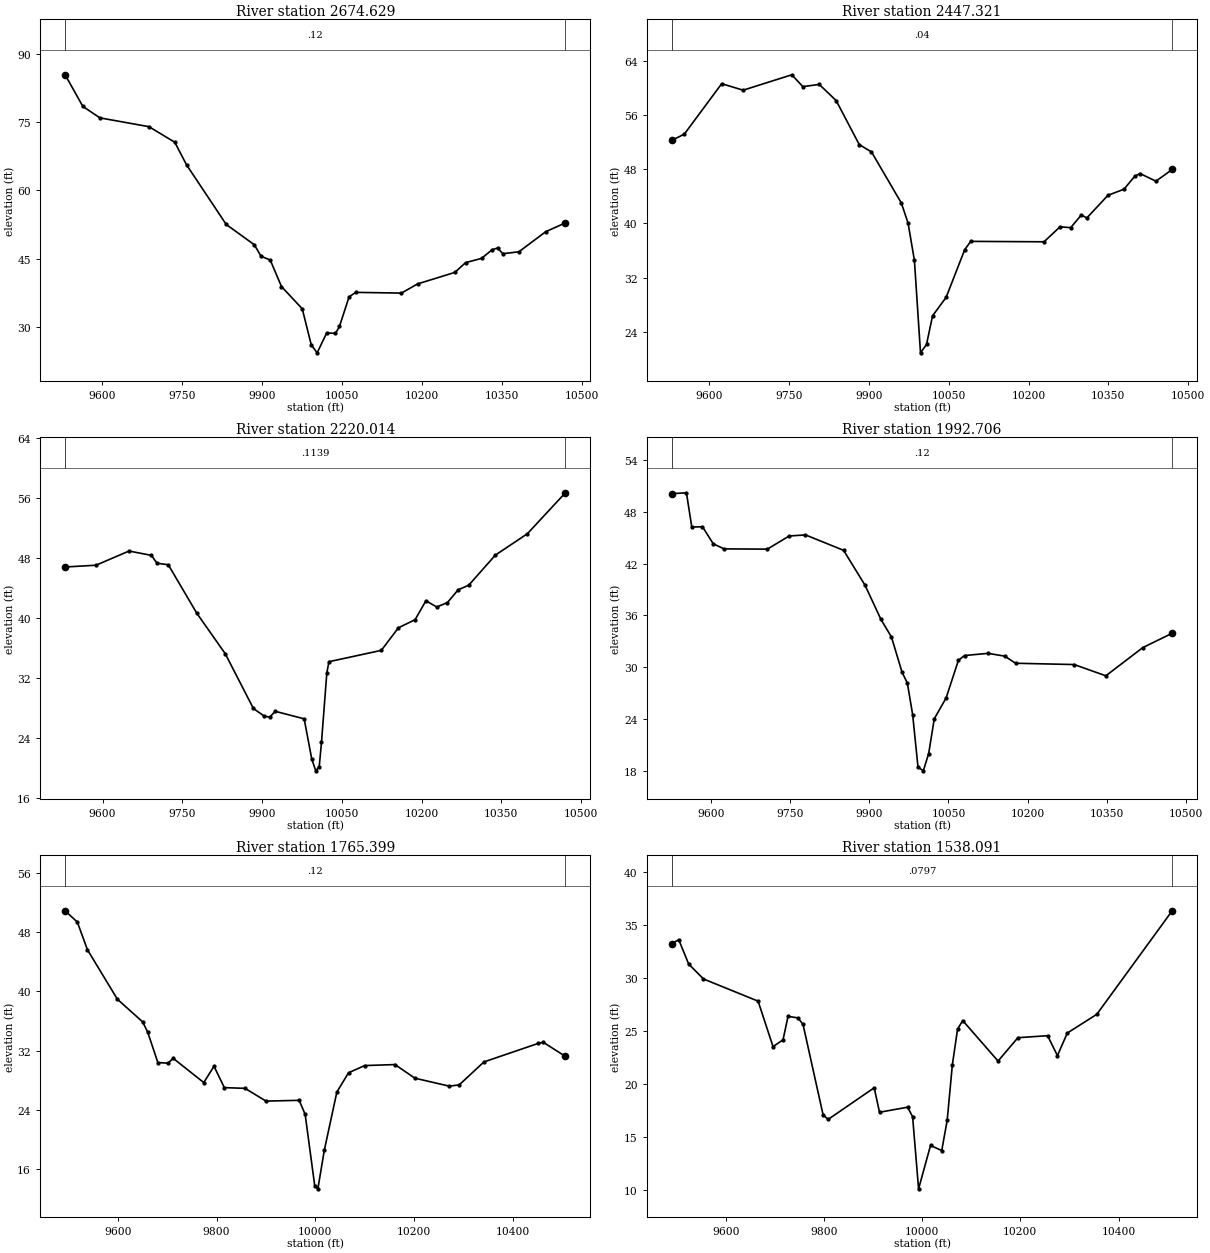
Type RM Length L Ch R = 1 ,2674.629,227.307500,227.307500,227.307500
XS GIS Cut Line= 6
1003743.82397177772669.1834693541004020.87552278772788.139251137
1004102.67680971772846.1069778631004197.11009031772939.259396353
1004240.64500137772963.9541091931004591.79240267772979.942719254
#Sta/Elev= 30
9531.24885.340429564.44378.417899596.38775.901669688.42173.967349736.75270.55776
9758.77765.606649833.18552.545149885.80648.09826 9898.2945.592659915.61944.75055
9936.71138.939619975.62834.068469992.46226.1808410003.5124.4205310021.44 28.7861
10037.8428.6820210045.2830.1918710063.3836.6882110075.7837.6681710161.5437.51107
10191.57 39.512810261.5742.0466210281.5744.1776610311.57 45.114310331.5747.01958
10341.5747.3834710351.5746.13803 10381.646.5622610431.7450.9535810468.6852.89737
#Mann= 3 , 0 , 0
9531.248    0.12       09531.248    0.12       010468.68    0.12       0
#XS Ineff= 2 , 0
       0                               0
Bank Sta=9531.248,10468.68
Exp/Cntr=0.3,0.1

Type RM Length L Ch R = 1 ,2447.321,227.307500,227.307500,227.307500
XS GIS Cut Line= 6
1003661.85509458773230.5929854841003982.33223251 773172.93663887
1004055.76686088773127.6613308971004115.22715545773046.056254384
1004227.11629569772991.8904046441004525.55628113772975.618716023
#Sta/Elev= 30
9529.96652.238659553.18653.144899623.42560.584339663.73659.624389755.26561.89685
9775.79760.15156 9806.7860.473129838.53758.092269881.94351.601089904.89850.52471
9961.01942.990269973.67640.02074 9985.5734.531659997.00220.90437 10008.322.13771
10019.6326.3590110045.1329.0794110080.07 36.111310091.3837.3372310229.0937.27402
 10259.239.4861210279.2739.3594110299.3341.2469810309.3440.7759310349.35 44.1347
10379.36 45.025810399.3746.9199410409.3747.3388710439.3946.2123510469.9647.93377
#Mann= 3 , 0 , 0
9529.966    0.04       09529.966    0.04       010469.96    0.04       0
#XS Ineff= 2 , 0
       0                               0
Bank Sta=9529.966,10469.96
Exp/Cntr=0.3,0.1

Type RM Length L Ch R = 1 ,2220.014,227.307500,227.307500,227.307500
XS GIS Cut Line= 6
1003858.57524109773319.3273427541004254.50535768773194.839102012
1004359.73850979 773105.341323831004443.28847167773067.498582718
 1004576.2277396773052.4601330241004735.89523244773067.202888322
#Sta/Elev= 30
 9529.4946.788979587.48447.022429649.719 48.91249691.79648.337819702.36347.28123
9723.49647.092059777.12240.633929830.76335.228489883.66627.93467  9904.226.91253
9914.46626.790999924.73227.559739979.15326.558739993.38421.21343   1000119.62903
10007.5120.2021810011.7523.4329810021.7532.6675310025.7934.1703310124.2735.67896
10156.4738.69032 10187.839.7656510208.1742.2880610228.5441.4585410248.6842.04941
10268.7343.7447310288.7744.36426 10338.848.3698610398.9551.21567 10470.556.67564
#Mann= 3 , 0 , 0
 9529.49  0.1139       0 9529.49  0.1139       0 10470.5  0.1139       0
#XS Ineff= 2 , 0
       0                               0
Bank Sta=9529.49,10470.5
Exp/Cntr=0.3,0.1

Type RM Length L Ch R = 1 ,1992.706,227.307500,227.307500,227.307500
XS GIS Cut Line= 6
1003767.94150853773379.7984053521004163.42184223773297.322778123
1004249.02459733773307.953079871 1004338.0195474773355.288436672
1004414.38329249773377.363040177 1004690.6127464 773399.65652026
#Sta/Elev= 30
9525.56650.122089553.04650.223939563.20246.251459583.51346.281869603.90744.30794
9624.37143.716059706.55643.687989747.85745.210169778.83345.33829 9851.1143.54755
 9891.7339.503939921.83935.548529941.88333.495629961.95829.411249972.04528.14835
9982.13224.467989992.21818.4020210002.3117.9716510012.4919.9819810023.11 24.0108
10045.61 26.431610068.8730.7940110080.4931.3459210124.9131.5994410156.6831.27657
10177.2630.4503610288.3930.29997 10348.528.9965510418.6432.2674710474.3633.92991
#Mann= 3 , 0 , 0
9525.566    0.12       09525.566    0.12       010474.36    0.12       0
#XS Ineff= 2 , 0
       0                10188.55       0
Bank Sta=9525.566,10474.36
Exp/Cntr=0.3,0.1

Type RM Length L Ch R = 1 ,1765.399,227.307500,227.307500,227.307500
XS GIS Cut Line= 6
1003790.61003713773672.7676349951004161.97410307773583.169058422
 1004234.5674388773551.5379052261004323.76223391773485.259768949
1004389.05789469773462.4099981261004759.84336437773461.264262559
#Sta/Elev= 30
 9493.0250.923629517.79349.394879538.10845.666899599.05338.934079650.24735.87334
9660.48634.468849680.96330.372139701.60830.282269711.95230.946379774.01727.66266
9794.745 29.86559815.72226.974789857.67726.873869900.164 25.14859967.40525.25359
9979.52623.34822    9999 13.638610005.27 13.265510018.2918.4846310043.7726.37594
10067.4128.9849810100.06 29.959510161.5830.0956610201.82 28.253210271.8527.16842
10291.8627.3506610341.8730.4545510451.9732.9646710461.9833.12152 10506.931.20156
#Mann= 3 , 0 , 0
 9493.02    0.12       0 9493.02    0.12       0 10506.9    0.12       0
#XS Ineff= 2 , 0
       09834.164        10124.56       0
Bank Sta=9493.02,10506.9
Exp/Cntr=0.3,0.1

Type RM Length L Ch R = 1 ,1538.091,227.307500,227.307500,227.307500
XS GIS Cut Line= 6
1003831.23978763773841.1069574041004181.22842209773780.929049683
1004363.93072163 773693.277984371004453.50883344773668.514276105
1004633.23094987773648.9943714671004818.46968803773652.827821946
#Sta/Elev= 30
9490.63233.270369504.49633.629179524.64831.334989554.876 29.92059666.03127.82908
 9696.4823.532959716.84224.176119727.02326.394229747.38526.243199757.56625.62602
9798.50817.06989 9808.7916.665369902.49619.646949913.28917.337049970.46617.81386
9980.68116.915839992.86210.1058110017.1514.1985310040.0313.7233610051.1316.58992
10061.6621.8295210072.1925.1752710082.7325.9959610154.6622.17114 10195.124.37805
10255.5724.5655910275.62 22.683110295.6624.8157610355.7326.5843210509.3136.36063
#Mann= 3 , 0 , 0
9490.632  0.0797       09490.632  0.0797       010509.31  0.0797       0
#XS Ineff= 2 , 0
       09890.365        10084.84       0
Bank Sta=9490.632,10509.31
Exp/Cntr=0.3,0.1

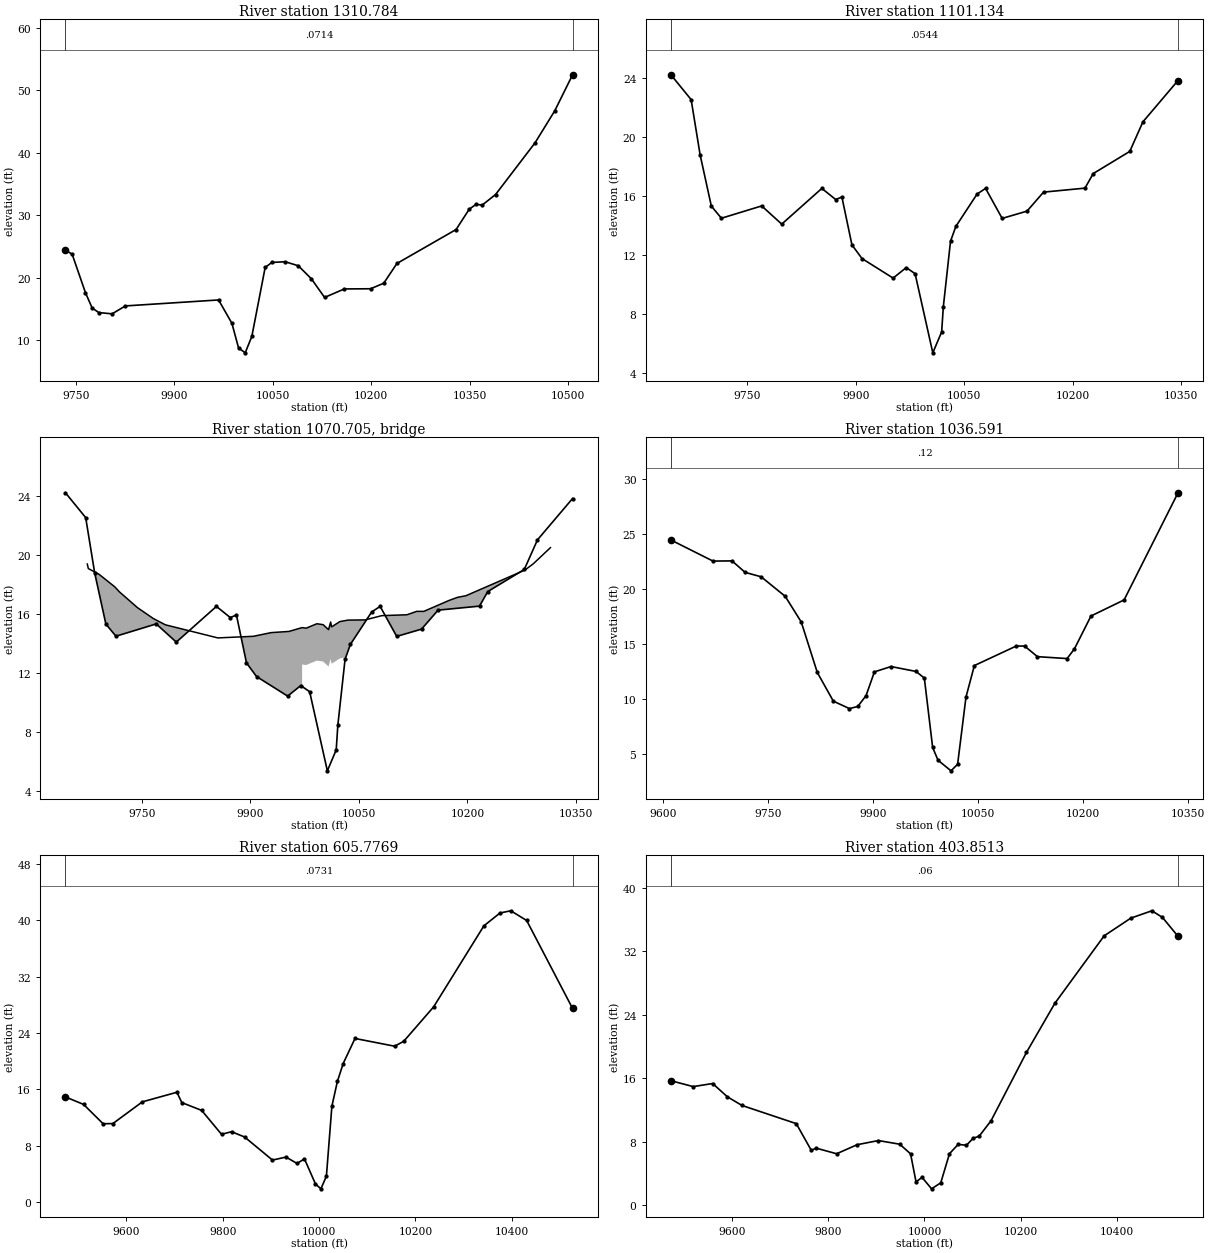
Type RM Length L Ch R = 1 ,1310.784,209.649500,209.649500,209.649500
XS GIS Cut Line= 3
1004094.94027707773875.5962794131004424.54215285773930.717412233
1004862.13645214773956.590597004
#Sta/Elev= 30
9734.23224.403519744.431 23.74329764.70917.577729774.84815.143859784.98714.40273
9805.26514.197979825.54215.465839967.48716.421879987.76412.692259997.9038.748145
10008.047.95538710018.1810.5974910038.4621.62164 10048.622.4260410068.8722.53987
 10088.921.8986910108.9419.8004210128.97 16.822910159.0318.18568 10199.118.21242
10219.1319.1052910239.1722.2610510329.3227.6971910349.3630.9547310359.3831.70259
10369.3931.6329910389.4333.2975410449.53 41.567410479.5946.6945710506.7752.46883
#Mann= 3 , 0 , 0
9734.232  0.0714       09734.232  0.0714       010506.77  0.0714       0
#XS Ineff= 2 , 0
       09928.148        10072.91       0
Bank Sta=9734.232,10506.77
Exp/Cntr=0.3,0.1

Type RM Length L Ch R = 1 ,1101.134,64.542800,64.542800,64.542800
XS GIS Cut Line= 5
1004094.94027707773886.8454902021004173.68475252773963.340123489
1004285.05193919774070.2076258661004418.91754746774164.700996414
1004657.40081596 774297.44168359
#Sta/Elev= 30
9644.50424.20042 9672.4722.51675 9684.9118.763379700.35415.298769714.29514.47407
9769.96815.308659797.68714.075189853.12516.495889872.22715.743789880.84415.90986
9894.70312.669029908.56211.742669951.62610.414839969.77311.128419982.01310.71334
10006.49 5.3477810018.736.76777510020.998.45353210030.9712.9132710038.33 13.9191
 10067.716.1155810079.4516.4969510102.3414.4621810136.6814.9554910159.5616.24368
10216.7916.5150410228.2317.5023210278.7219.00397 10296.921.0089610345.4323.81253
#Mann= 3 , 0 , 0
9644.504  0.0544       09644.504  0.0544       010345.43  0.0544       0
#XS Ineff= 2 , 0
       09972.285        10035.68       0
Bank Sta=9644.504,10345.43
Exp/Cntr=0.3,0.1

Type RM Length L Ch R = 3 ,1070.705,,,
BEGIN DESCRIPTION:
END DESCRIPTION:
Bridge Culvert--1,0,-1,-1, 0
Deck Dist Width WeirC Skew NumUp NumDn MinLoCord MaxHiCord MaxSubmerge Is_Ogee
22.271400,20.000000,2.6,0, 35, 35, , , 0.95, 0, 0,0,,
 9674.67 9676.14 9690.76 9712.75 9718.93 9743.84 9765.75 9782.52 9855.11 9904.30
 9928.90 9953.50 9971.59 9971.59 9977.08 9991.9910000.6410008.1310011.0610012.34
10023.9010035.4510036.3310036.3310058.5610081.7510116.5710129.9410139.7910174.67
10186.3210197.9810279.5610291.2210314.82
   19.37   19.06   18.68   17.82   17.49   16.42   15.68   15.25   14.36   14.47
   14.72   14.80   15.06   15.06   15.02   15.32   15.26   14.92   15.44   15.11
   15.47   15.57   15.57   15.57   15.58   15.87   15.93   16.16   16.16   16.90
   17.11   17.22   18.96   19.39   20.48
 -980.63 -980.94 -981.32 -982.18 -982.51 -983.58 -984.32 -984.75 -985.64 -985.53
 -985.28 -985.20 -984.94   12.56   12.52   12.82   12.76   12.42   12.94   12.61
   12.97   13.07   13.07 -984.43 -984.42 -984.13 -984.07 -983.84 -983.84 -983.10
 -982.89 -982.78 -981.04 -980.61 -979.52
 9674.67 9676.14 9690.76 9712.75 9718.93 9743.84 9765.75 9782.52 9855.11 9904.30
 9928.90 9953.50 9974.59 9974.59 9977.08 9991.9910000.6410008.1310011.0610012.34
10023.9010035.4510041.7010041.7010058.5610081.7510116.5710129.9410139.7910174.67
10186.3210197.9810279.5610291.2210314.82
   19.37   19.06   18.68   17.82   17.49   16.42   15.68   15.25   14.36   14.47
   14.72   14.80   15.07   15.07   15.02   15.32   15.26   14.92   15.44   15.11
   15.47   15.57   15.57   15.57   15.58   15.87   15.93   16.16   16.16   16.90
   17.11   17.22   18.96   19.39   20.48
 -980.63 -980.94 -981.32 -982.18 -982.51 -983.58 -984.32 -984.75 -985.64 -985.53
 -985.28 -985.20 -984.93   12.57   12.52   12.82   12.76   12.42   12.94   12.61
   12.97   13.07   13.07 -984.43 -984.42 -984.13 -984.07 -983.84 -983.84 -983.10
 -982.89 -982.78 -981.04 -980.61 -979.52
BR Coef=-1 , 0 , 0 ,, 0 ,,,0.8,0,1,0,
WSPro=,,,, 1 ,,,, 0 ,,,, 0 ,,,,-1 ,-1 ,-1 , 0 , 0 , 0 , 0 , 0
BC Design=,, 0 ,, 0 ,,,,,,

Type RM Length L Ch R = 1 ,1036.591,430.814600,430.814600,430.814600
XS GIS Cut Line= 5
1003992.57245898773982.4637817891004214.18191129774106.205100358
 1004345.7976774774190.5741811841004440.29104793774252.444840461
 1004610.1541307774359.312342867
#Sta/Elev= 30
9611.73724.491669671.78422.574039698.98722.590819717.59721.548529740.50421.14632
9774.86419.37045 9797.7717.034959820.67712.444169843.5849.8373479866.5259.161329
9878.4039.3553729890.28110.34172 9902.16 12.50049925.91612.984529961.55112.53991
9973.42911.937189985.3075.628446 9993.034.46119210011.563.50272210020.944.106763
10032.8910.2142610044.8413.0737810104.6114.8498210116.5614.8474110134.8413.88433
10177.1913.7106810187.6614.5923910211.2917.5805410258.5419.0417710335.5228.78425
#Mann= 3 , 0 , 0
9611.737    0.12       09611.737    0.12       010335.52    0.12       0
#XS Ineff= 2 , 0
       0 9974.23        10040.93       0
Bank Sta=9611.737,10335.52
Exp/Cntr=0.3,0.1

Type RM Length L Ch R = 1 ,605.7769,201.925600,201.925600,201.925600
XS GIS Cut Line= 6
1003857.97633943774348.4141601791004275.14730049774448.313220465
1004382.97415372774596.7946238351004449.17330224774661.002933535
1004583.52593692774746.0039012451004752.35217505774823.190975455
#Sta/Elev= 30
9473.63714.920379511.19913.86056 9551.7811.108399572.07111.135659633.30814.22378
 9704.9815.584569715.21814.114299756.40713.007969797.5719.6111919818.4359.976195
9845.4179.2335629903.3875.9467029931.5116.3754259954.4345.4644959969.7766.120383
9992.6262.55553110003.931.85990210015.333.65316910026.7313.6026410038.12 17.1163
 10050.219.6699910074.7223.2307310157.0822.12838   1017622.8379410237.9327.71764
10342.3639.2425810375.8241.0636810398.1341.3768810431.0839.99712 10526.427.49633
#Mann= 3 , 0 , 0
9473.637  0.0731       09473.637  0.0731       0 10526.4  0.0731       0
#XS Ineff= 2 , 0
       0                               0
Bank Sta=9473.637,10526.4
Exp/Cntr=0.3,0.1

Type RM Length L Ch R = 1 ,403.8513,201.925700,201.925700,201.925700
XS GIS Cut Line= 6
1003679.10900562774484.9852638831003893.25575753774522.986953951
1004060.25319794774577.2914339571004205.05088602774652.096851529
1004439.83297085774809.8987818181004634.51837154774903.322639199
#Sta/Elev= 30
9472.262 15.67899518.68714.936589559.15215.325849589.50213.663269620.11712.55937
9733.20110.26399 9764.37 6.90046 9774.767.1673349817.2086.4630359859.9837.607028
9904.1438.1277769948.5117.6685159971.0956.4506419982.4682.909073 9994.943.486228
10014.812.03526710033.942.80042210052.06 6.4698410070.197.64775610087.377.531474
 10101.48.42366810113.768.67212810138.4710.6152810212.2219.2403610271.4425.45186
10373.9733.9572710429.5336.1978810473.43 37.124210495.3836.2859410527.7833.89981
#Mann= 3 , 0 , 0
9472.262    0.06       09472.262    0.06       010527.78    0.06       0
#XS Ineff= 2 , 0
       0                               0
Bank Sta=9472.262,10527.78
Exp/Cntr=0.3,0.1

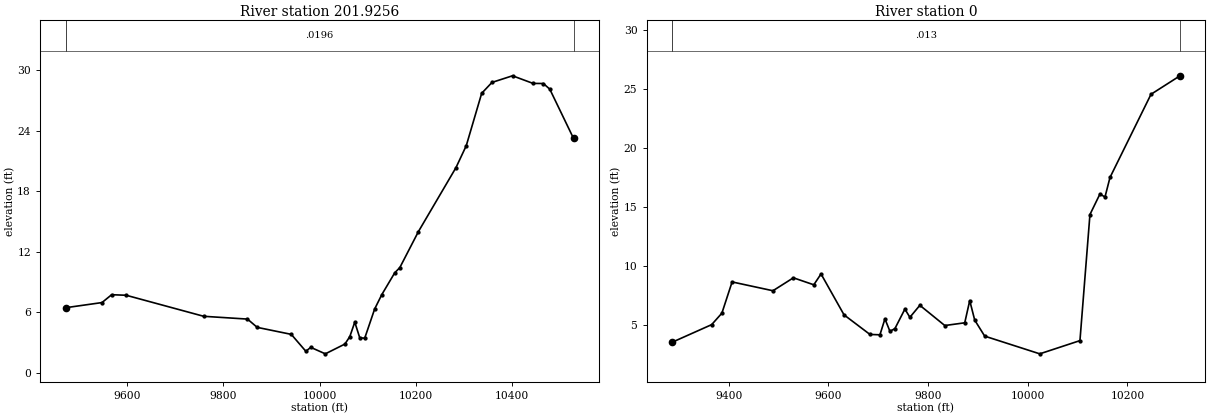
Type RM Length L Ch R = 1 ,201.9256,201.925600,201.925600,201.925600
XS GIS Cut Line= 6
1003589.59175784774754.1932421551003882.01283789774789.887862935
1004178.16318227774838.8171113261004238.04217656774854.556586908
1004311.94570384774878.3605178581004613.79514607774992.503420037
#Sta/Elev= 30
9471.449 6.433399547.3266.9454669567.4517.7243899597.6377.6707879758.9835.584559
9850.0745.3081189870.3224.4870829941.1893.794166 9971.562.1144629981.6842.506253
10012.06 1.8627710052.842.83513710063.03 3.5751310073.335.00513910083.673.452209
10094.013.41282710114.69 6.3110210129.627.74019610156.499.898169   1016710.40943
10205.8113.9886910283.9220.32797 10305.322.4988910337.3727.6911410358.7628.77033
10401.5229.4296610444.2828.6729410465.6728.6634810479.04 28.105910528.5223.21925
#Mann= 3 , 0 , 0
9471.449  0.0196       09471.449  0.0196       010528.52  0.0196       0
#XS Ineff= 2 , 0
       0 9880.85        10073.47       0
Bank Sta=9471.449,10528.52
Exp/Cntr=0.3,0.1

Type RM Length L Ch R = 1 ,       0,0.000000,0.000000,0.000000
XS GIS Cut Line= 6
1003397.24906889774940.2636624131003784.57452941775026.163940102
1004028.62250483775031.9249651731004230.76470786775012.158716038
1004291.81958473775018.9425912351004399.12686062775055.311504975
#Sta/Elev= 30
9286.3783.5605219366.0185.0577349386.5046.027509 9406.998.6691899488.9347.923588
9529.9069.0184589570.8788.4269769585.3689.3451219631.553 5.882639683.5414.227149
 9703.564.1974289713.5695.5462039723.5794.4945799733.588 4.721499753.6076.372091
9763.6165.6763949783.6356.6922829833.6674.9813749873.667 5.212159883.6677.092143
9893.6675.4405199913.6674.08528110024.162.58693210104.773.70550210124.8114.36979
10144.91 16.110310154.9715.8474110165.0317.5046310247.2824.5406410305.4926.10661
#Mann= 3 , 0 , 0
9286.378   0.013       09286.378   0.013       010305.49   0.013       0
#XS Ineff= 2 , 0
       09938.394        10073.17       0
Bank Sta=9286.378,10305.49
Exp/Cntr=0.3,0.1